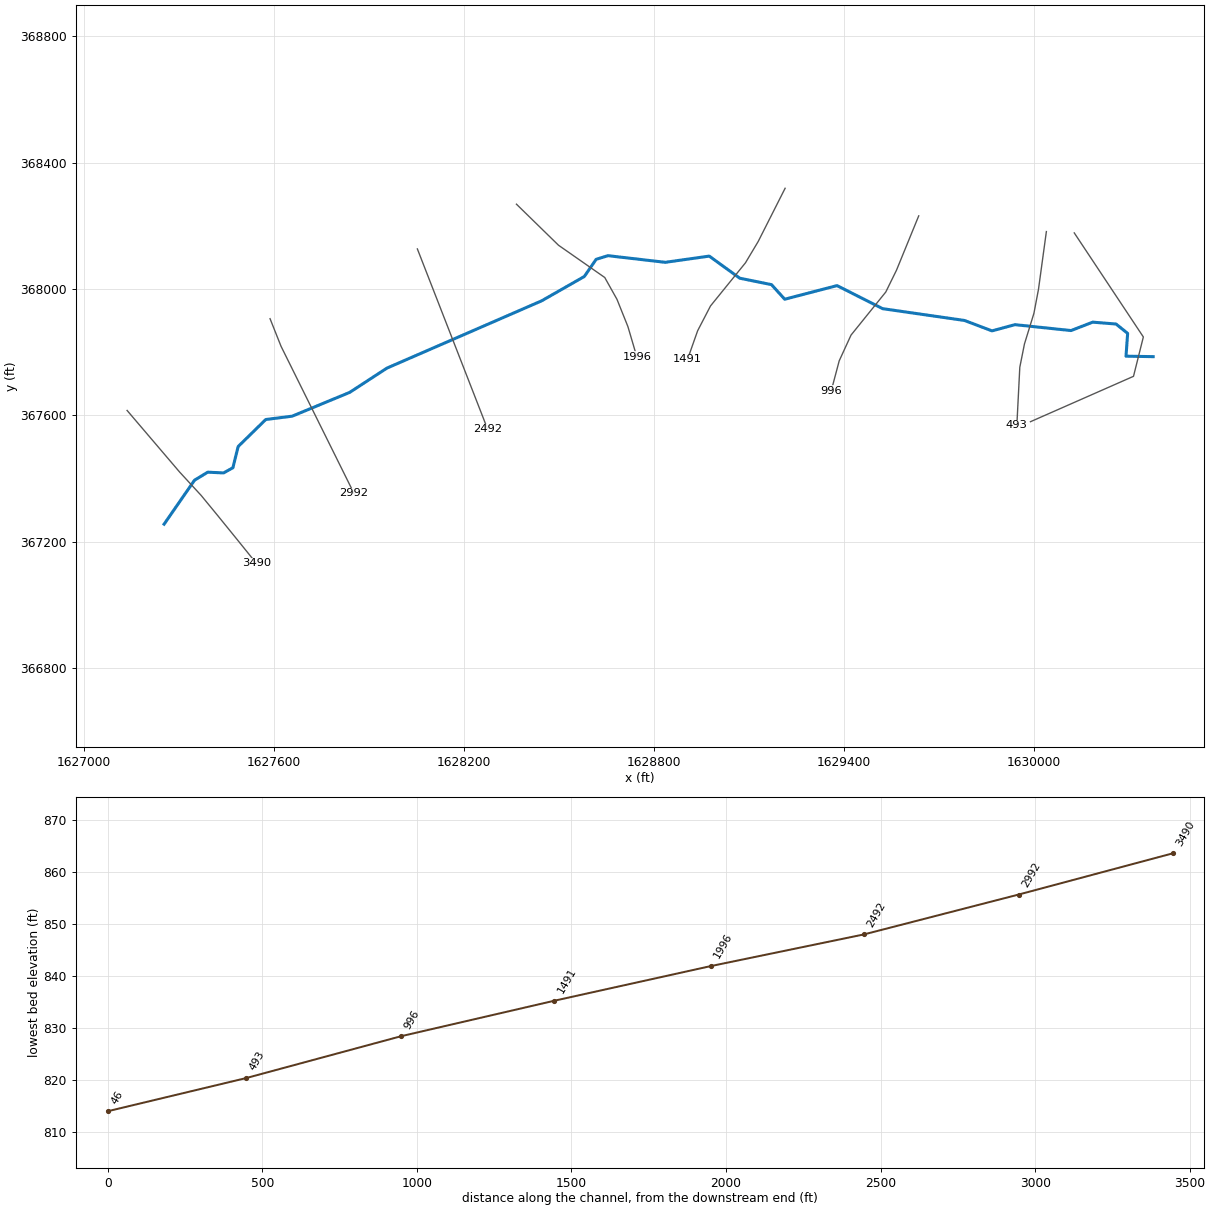
--- WEEKLYRN.prj (project) ---

Proj Title=WEEKLYRN
Current Plan=p01
Default Exp/Contr=0,0
English Units
Geom File=g01
Flow File=f01
Plan File=p01
BEGIN DESCRIPTION:
---------- MODELED AS PART OF WVEMD CTP PROGRAM, 2023----------
Stream Name: Weekly Run
Flood Zone:  AFH
Wetzel County, WV
HEC-RAS Version: RAS 6.3
Vertical Datum: NAVD88
Projection: NAD 1983 StatePlane West Virginia S FIPS 4702 (US Feet)
Terrain: 1-meter West Virginia FEMA R3 South Central (collected 2018-2020)
Land Use: 2019 NLCD
Hydrologic Method:
WV SIR2010-5033 regression equations
Additional Model Notes:
None
END DESCRIPTION:
DSS Export Rating Curves= 0
DSS Export Rating Curve Sorted= 0
DSS Export Volume Flow Curves= 0
DXF OffsetX= 0
DXF OffsetY= 0
DXF ScaleX= 0
DXF ScaleY= 0

--- WEEKLYRN.p01 (plan) ---

Plan Title=Floodplain
Program Version=6.30
Short Identifier=Floodplain
Geom File=g01
Flow File=f01
Subcritical Flow
K Sum by GR= 0
Std Step Tol= 0.01
Critical Tol= 0.01
Num of Std Step Trials= 20
Max Error Tol= 0.3
Flow Tol Ratio= 0.001
Split Flow NTrial= 30
Split Flow Tol= 0.02
Split Flow Ratio= 0.02
Log Output Level= 0
Friction Slope Method= 1
Unsteady Friction Slope Method= 2
Unsteady Bridges Friction Slope Method= 1
Parabolic Critical Depth
Global Vel Dist= 0 , 0 , 0
Global Log Level= 0
CheckData=True
Encroach Param=-1 ,0,0, 0
Mapping Interval=1HOUR
Computation Time Step Use Courant=        0
Computation Time Step Use Time Series=    0
Computation Time Step Count To Double=0
Computation Time Step Max Doubling=0
Computation Time Step Max Halving=0
Computation Time Step Residence Courant=0
Run HTab= 0
Run UNet= 0
Run Sediment= 0
Run PostProcess= 0
Run WQNet= 0
Run RASMapper= 0
UNET Theta= 0
UNET Theta Warmup= 0
UNET ZTol= 0
UNET ZSATol= 0
UNET MxIter= 0
UNET Max Iter WO Improvement= 0
UNET MaxInSteps= 0
UNET DtIC= 0
UNET DtMin= 0
UNET MaxCRTS= 0
UNET WFStab= 0
UNET SFStab= 0
UNET WFX= 1
UNET SFX= 1
UNET Gravity=32.17405
UNET 1D Methodology=Finite Difference
UNET DSS MLevel= 1
UNET Pardiso=0
UNET DZMax Abort= 0
UNET Use Existing IB Tables= 0
UNET Froude Reduction=False
UNET Froude Limit= 0
UNET Froude Power= 0
UNET D1 Cores= 0
UNET WindReference=Eulerian
UNET WindDragFormulation=Hsu (1988)
UNET D2 Coriolis=0
UNET D2 Cores= 0
UNET D2 Theta= 1
UNET D2 Theta Warmup= 1
UNET D2 Z Tol= 0.01
UNET D2 Volume Tol= 0.01
UNET D2 Max Iterations= 20
UNET D2 Equation= 0
UNET D2 RampUpFraction=0.1
UNET D2 TimeSlices= 1
UNET D2 Turbulence Formulation=Non-Conservative (original)
UNET D2 Eddy Viscosity=0.3
UNET D2 Transverse Eddy Viscosity=0.1
UNET D2 Smagorinsky Mixing=0
UNET D2 BCVolumeCheck=0
UNET D2 Cores=0
UNET D2 SolverType=PARDISO (Direct)
UNET D2 Minimum Iterations= 3
UNET D2 Maximum Iterations= 30
UNET D2 Restart Number= 10
UNET D2 Relaxation Coeff=1.3
UNET D2 SOR Precondition Iterations= 10
UNET D2 ILUT Maximum Fill= 8
UNET D2 ILUT Tolerance=1E-08
UNET D2 Convergence Tolerance=0.00001
UNET D1D2 MaxIter= 0
UNET D1D2 ZTol=0.01
UNET D1D2 QTol=0.1
UNET D1D2 MinQTol=1
Write IC File= 0
Write IC File at Fixed DateTime=0
Write IC File at Sim End=0
Echo Input=False
Echo Parameters=False
Echo Output=False
Write Detailed= 0
HDF Write Warmup=0
HDF Write Time Slices=0
HDF Flush=0
HDF Compression= 1
HDF Chunk Size= 1
HDF Spatial Parts= 1
HDF Use Max Rows=0
HDF Fixed Rows= 1
Calibration Method= 0
Calibration Iterations= 20
Calibration Max Change=0.05
Calibration Tolerance=0.2
Calibration Maximum=1.5
Calibration Minimum=0.5
Calibration Optimization Method= 1
WQ AD Non Conservative
WQ ULTIMATE=-1
WQ Max Comp Step=1HOUR
WQ Output Interval=15MIN
WQ Output Selected Increments= 0
WQ Output face flow=0
WQ Output face velocity=0
WQ Output face area=0
WQ Output face dispersion=0
WQ Output cell volume=0
WQ Output cell surface area=0
WQ Output cell continuity=0
WQ Output cumulative cell continuity=0
WQ Output face conc=0
WQ Output face dconc_dx=0
WQ Output face courant=0
WQ Output face peclet=0
WQ Output face adv mass=0
WQ Output face disp mass=0
WQ Output cell mass=0
WQ Output cell source sink temp=0
WQ Output nsm pathways=0
WQ Output nsm derived pathways=0
WQ Create Restart=0
WQ Fixed Restart=0
WQ System Summary=0
WQ Write To DSS=0
Sorting and Armoring Iterations= 10
XS Update Threshold= 0.02
Bed Roughness Predictor= 0
Hydraulics Update Threshold= 0.02
Energy Slope Method= 1
Volume Change Method= 1
Sediment Retention Method= 0
Sediment TS Multiplier= 1
Warm Up Method= 0
XS Weighting Method= 0
Number of US Weighted Cross Sections= 1
Number of DS Weighted Cross Sections= 1
Upstream XS Weight=0
Main XS Weight=1
Downstream XS Weight=0
Number of DS XS's Weighted with US Boundary= 1
Upstream Boundary Weight= 1
Weight of XSs Associated with US Boundary= 0
Number of US XS's Weighted with DS Boundary= 1
Downstream Boundary Weight= 0.5
Weight of XSs Associated with DS Boundary= 0.5
Percentile Method= 0
Sediment Output Level= 3
Mass or Volume Output= 0
Output Increment Type= 1
Profile and TS Output Increment= 1
Transport Output Increment 1
XS Output Flag= 0
XS Output Increment= 10
Read HDF5 Sediment Hotstart= 0
Sediment Hotstart Type= 0
Write Gradation File= 0
Read Gradation Hotstart= 0
Write HDF5 File= 1
Write Binary Output= 1
Write DSS Sediment File= 0
DSS Sediment Output Type= 1
SV Curve= 0
Specific Gage Flag= 0
Subcell Erosion Methods= 0
Subcell Deposition Methods= 0
Advection Scheme= 1
Matrix Solver= 0
Implicit Weighting Factor= 1
Maximum Outer Loop Convergence Iterations= 5
Convergence Maximum Absolute= 0.001
Convergence RMSE= 0.0001
Grain Fractions Max Abs Error= 0.001
Max Subgrid Regions= 1
Max Subgrid Length Scale= 3.402823E+38
Initial Layer Thickness= 3.402823E+38
Min Layer Thickness= 3.402823E+38
Max Layer Thickness= 3.402823E+38
Number of Layers= 5

--- WEEKLYRN.f01 (steady flow) ---

Flow Title=Flow
Program Version=6.31
Number of Profiles= 1
Profile Names=F01pct
River Rch & RM=WEEKLYRN,Main,3490
     679
River Rch & RM=WEEKLYRN,Main,2492
     762
Boundary for River Rch & Prof#=WEEKLYRN,Main            , 1
Up Type= 0
Dn Type= 3
Dn Slope=0.01603
DSS Import GetInterval= 0
DSS Import GetPeak= 0
DSS Import FillOption= 0

--- WEEKLYRN.g01 (geometry) ---

Geom Title=Geometry
Program Version=6.30

River Reach=WEEKLYRN        ,Main
Reach XY= 30
1627253.03799958367255.7470010911627349.13699958367394.918001122
1627390.91399958367420.3910010991627440.84199959367418.014001094
 1627470.3919996367434.3170011231627487.03499959367501.568001102
1627574.32399959 367587.159001111627657.87799961367597.688001107
 1627839.5899996367673.0900011021627957.10799958367749.851001107
1628445.86299958367962.811001122 1628580.7029996368039.911001127
1628618.06399958368094.255001114 1628655.4259996368105.802001118
1628836.45899959368084.7440011161628975.37499957368104.444001132
 1629071.8349996368034.4760011311629172.03199958368014.098001139
1629213.80799959367967.905001129 1629379.2169996368011.041001108
 1629523.2279996367938.016001078 1629782.0409996367900.655001104
1629868.65099958367867.7090011131629941.33599958367887.409001109
1630118.29299957 367868.728001091630186.98841964367895.316101308
1630260.59513605367889.4440351961630297.26422566367859.761085916
1630292.11581726367787.6095637451630377.86144376367786.127066339

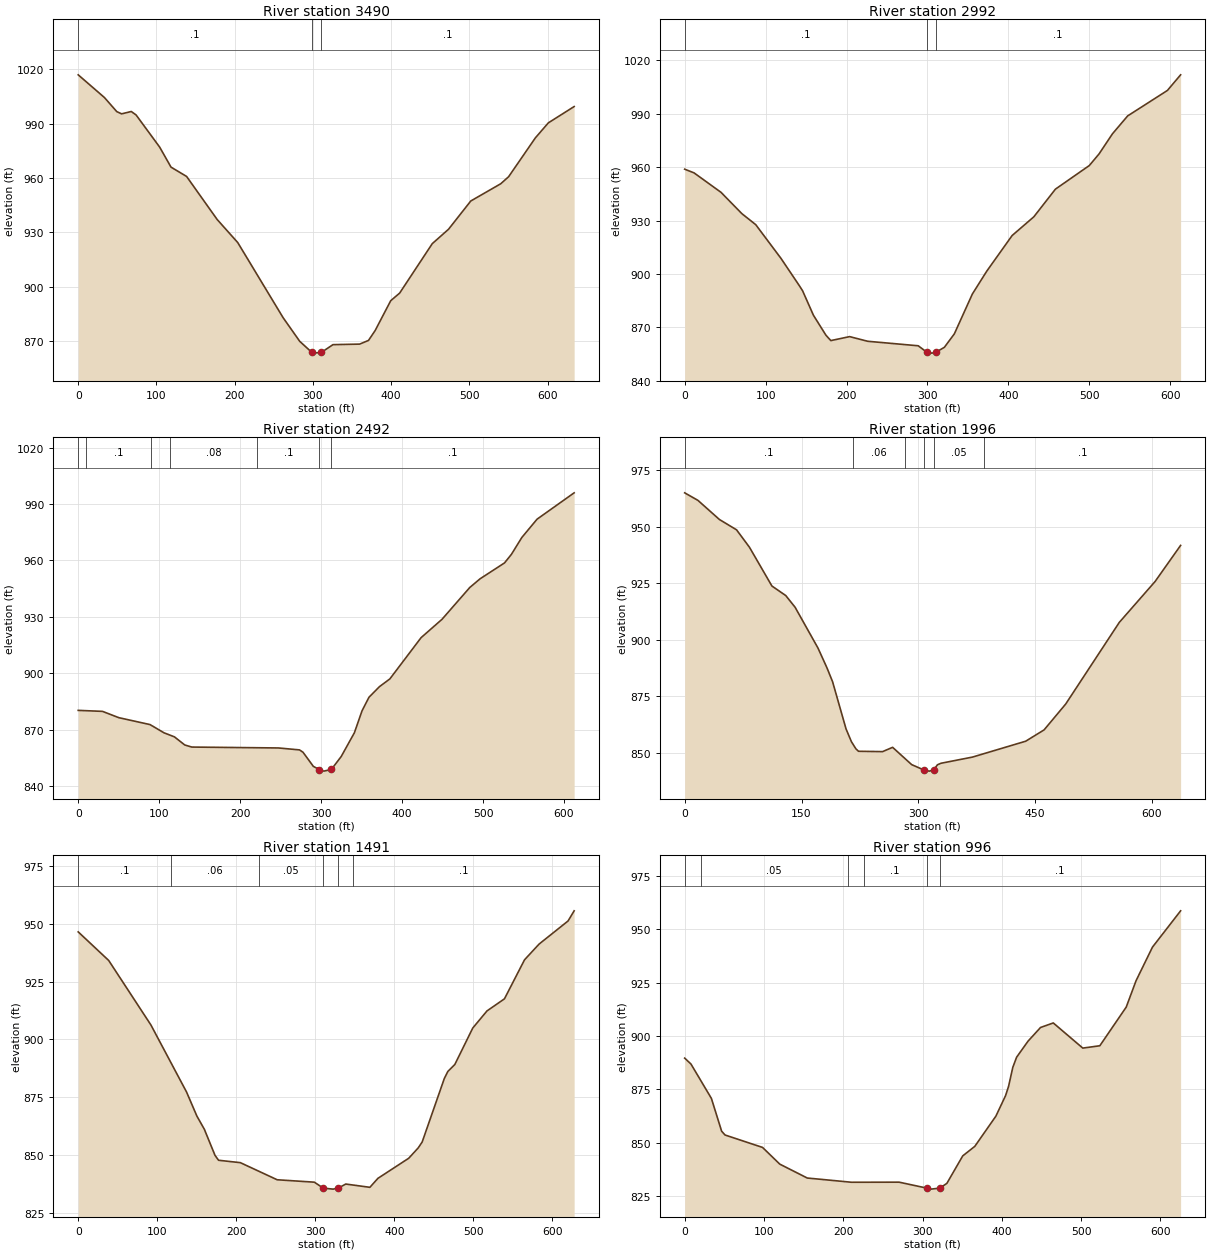
Type RM Length L Ch R = 1 ,3490    ,498.3,498.1,496.1
XS GIS Cut Line= 6
1627136.14881092367615.7975469231627302.22885934367420.652596012
1627369.95674226367346.9801711741627421.71943401367283.892042756
1627481.79805401367209.7005900891627544.78939784367131.506192669
#Sta/Elev= 30
       0 1016.88    33.5 1004.37    49.3   996.6    55.5  995.38    67.8  996.67
      74  994.75   104.1  977.04   118.6  966.01   138.5  960.88   177.6  937.14
   203.9  924.43   261.8  883.08   283.1  870.01  298.57863.9234   300.4  863.51
   310.7   863.9   325.6  868.18   359.7  868.48     371  870.52   379.5  875.97
   399.4  892.41   410.8  896.59   452.5  923.85   473.3  931.79   501.7  947.35
     540  956.85   550.1  960.75   584.2  982.11   600.8   990.4   633.8   999.4
#Mann= 3 ,-1,0
       0      .1       0  298.57    .045       0   310.7      .1       0
Bank Sta=298.57,310.7
XS Rating Curve= 0 ,0
Exp/Cntr(USF)=0,0
Exp/Cntr=0.3,0.1

Type RM Length L Ch R = 1 ,2992    ,500.5,500,499.2
XS GIS Cut Line= 6
1627587.82244825367906.2684226781627622.55663076 367818.84110409
1627661.36298358367740.4170483351627738.97765775 367583.57024917
1627811.04903592367437.9268396791627852.62375592367353.899448678
#Sta/Elev= 30
       0  958.89    11.6  956.81    44.9  945.89    70.7  933.91    87.8  927.74
     119   908.8   141.3  893.73   145.7  890.61   159.1  876.87   174.6  865.63
   180.6  862.64   203.8  864.87   226.1  862.26   288.6  859.72  299.61855.9886
     305   855.6  310.05855.9995   320.9  858.87   333.2  866.41   355.5  888.81
   373.3  901.65   404.6  921.63   431.4  932.13   458.1  947.67     500  960.94
     512  967.44   528.6  978.76   547.4  988.81   596.5  1003.1   612.8 1011.87
#Mann= 3 ,-1,0
       0      .1       0  299.61    .045       0  310.05      .1       0
Bank Sta=299.61,310.05
XS Rating Curve= 0 ,0
Exp/Cntr(USF)=0,0
Exp/Cntr=0.3,0.1

Type RM Length L Ch R = 1 ,2492    ,491.3,496,499.1
XS GIS Cut Line= 6
1628053.22866967368127.2207366681628087.20793243368039.845583335
1628146.10578051367888.3947707561628182.35045867 367795.19416976
1628209.53413133367725.2940470871628275.22724143367556.368203834
#Sta/Elev= 30
       0  880.27      30  879.74    50.1  876.39    88.7  872.71   105.9  868.35
   118.8  866.19   131.6  861.86   140.3  860.75   247.5  860.27   273.3  859.24
   277.6  858.01   290.4  850.48   297.8848.7914   303.3  847.95  312.63848.8268
   324.8  855.72   341.1  868.37   350.5  880.01   359.1  887.24     372  892.87
   384.9  897.01   423.5  918.97   449.3  928.71   483.6  945.64   496.4  950.29
   526.5  958.71   535.1  963.32   547.9  972.25   566.7  981.98   612.5     996
#Mann= 7 ,-1,0
       0     .06       0      10      .1       0      90     .05       0
  113.75     .08       0  221.25      .1       0   297.8    .045       0
  312.63      .1       0
Bank Sta=297.8,312.63
XS Rating Curve= 0 ,0
Exp/Cntr(USF)=0,0
Exp/Cntr=0.3,0.1

Type RM Length L Ch R = 1 ,1996    ,515.5,504.9,490.7
XS GIS Cut Line= 6
1628366.26019584368268.8431568441628499.08506143368138.902143762
1628645.23765625 368036.708778591628683.94689642367967.438904002
1628718.52130234367881.0043655931628746.73581284367785.033757001
#Sta/Elev= 30
       0  965.01      17  961.68    44.6  953.21    66.6  948.64    83.2  940.92
     112  923.78   129.8  919.55   141.8  914.37   171.2   896.3   182.7  887.57
   189.9  881.44   207.2  860.54   214.1  854.89   219.8  851.75   223.2  850.64
   254.1  850.49     267  852.39   291.5  844.73   307.3  842.35     314  841.86
   319.5842.3282   324.6  844.67     329  845.33   369.5  848.07   437.9   855.1
   461.5  860.11   489.2  871.53   558.1  907.69     604  925.76   636.8  941.75
#Mann= 6 ,-1,0
       0      .1       0  215.95     .06       0  283.15     .05       0
   307.3    .045       0   319.5     .05       0  384.36      .1       0
Bank Sta=307.3,319.5
XS Rating Curve= 0 ,0
Exp/Cntr(USF)=0,0
Exp/Cntr=0.3,0.1

Type RM Length L Ch R = 1 ,1491    ,493.8,495.4,495.2
XS GIS Cut Line= 6
1629215.08428559368319.1412845851629130.01391767368150.641949669
  1629089.759405368083.1158380061628979.41021626367946.674181759
1628938.73444459367868.1274228391628906.74238259367777.317893177
#Sta/Elev= 30
       0  946.53    38.6  934.15      92  906.25   137.1  877.24   150.2  866.82
   159.6  861.14   173.1  849.85   177.6  847.71   205.2  846.67   251.8  839.27
   298.8  838.23   310.2  835.65   322.5  835.22  328.94835.6266   338.6  837.42
   369.1     836   379.3  839.89   418.3  848.59   430.3  853.07   435.3  855.63
   463.3  883.09   467.8  886.16   476.6  889.15   499.3  904.92   517.3  912.33
   539.4  917.56   564.8  934.44   583.2  941.24   619.9  951.25   627.6  955.64
#Mann= 6 ,-1,0
       0      .1       0  117.11     .06       0  228.77     .05       0
   310.2    .045       0  328.94     .05       0  347.38      .1       0
Bank Sta=310.2,328.94
XS Rating Curve= 0 ,0
Exp/Cntr(USF)=0,0
Exp/Cntr=0.3,0.1

Type RM Length L Ch R = 1 ,996     ,499.1,502.5,505.7
XS GIS Cut Line= 6
1629637.21434684368231.8537295011629567.02518275368059.934125841
1629533.15517175367990.7757995871629423.32041767367854.336111844
1629385.99568917367772.9015634211629360.91732726367678.233445674
#Sta/Elev= 30
       0  889.66     7.9  886.92    33.7  870.83    46.6   855.5    50.9  853.72
    98.2  847.91   119.9  840.11   154.6   833.6   210.5  831.62   270.5  831.66
  305.19 828.902   310.6  828.41  321.85828.8684   330.7  831.11   350.7  843.95
   365.9   848.4   392.5  862.52   404.7  872.11   408.5  876.43   413.8  885.28
   418.6  890.06     433  897.56   448.8  903.98   464.9  906.11   502.1  894.35
   523.6  895.44   556.9  913.52   569.3  925.85     590  941.56   625.5  958.53
#Mann= 6 ,-1,0
       0      .1       0      20     .05       0  205.71     .06       0
  225.71      .1       0  305.19    .045       0  321.85      .1       0
Bank Sta=305.19,321.85
XS Rating Curve= 0 ,0
Exp/Cntr(USF)=0,0
Exp/Cntr=0.3,0.1

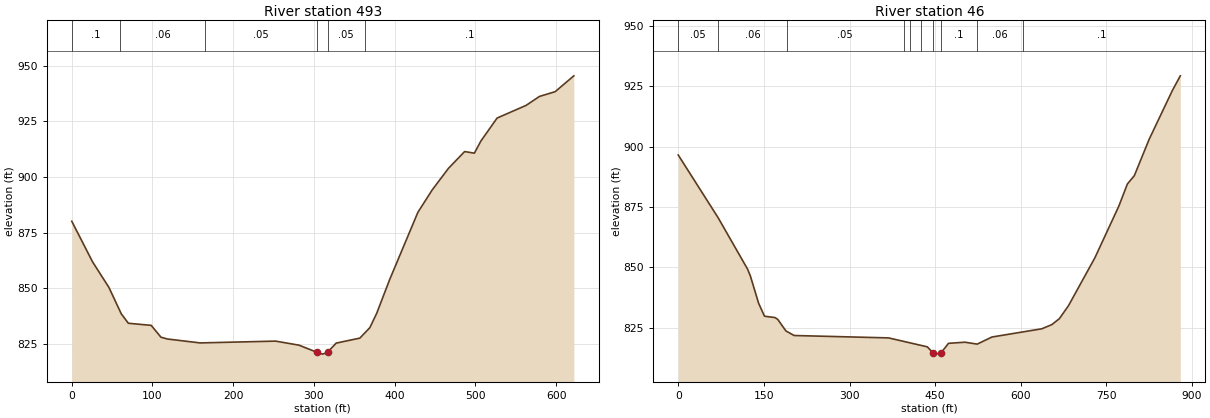
Type RM Length L Ch R = 1 ,493     ,442.5,447.1,446
XS GIS Cut Line= 6
1630040.50914392  368182.14516751630015.63484985367999.576635003
1630001.23363192 367923.586629511629971.29340309367826.416548252
1629956.58181834367752.5666303341629947.25375301 367569.43477875
#Sta/Elev= 30
       0  880.11    25.8  861.83      46  850.37    61.3   838.5    70.1  834.23
    98.4  833.29   110.5  827.96   118.6  827.15     159  825.39   252.5   826.2
   281.5  824.38  303.53821.2057   310.8  820.35  316.87821.1951   327.6  825.31
   356.9  827.55   369.3  832.26   377.8  838.74   393.8  853.85   428.8  884.13
   446.5  894.18   466.7  903.92   486.7  911.45   498.8  910.73   506.8  916.16
   526.9  926.52   562.9  932.22   579.3  936.22   598.9  938.39     622  945.51
#Mann= 6 ,-1,0
       0      .1       0      60     .06       0     165     .05       0
  303.53    .045       0  316.87     .05       0  363.29      .1       0
Bank Sta=303.53,316.87
XS Rating Curve= 0 ,0
Exp/Cntr(USF)=0,0
Exp/Cntr=0.3,0.1

Type RM Length L Ch R = 1 ,46      ,,,
XS GIS Cut Line= 4
1630128.63552317368177.880502676 1630346.8883362367848.441222948
1630315.77710125367723.835606922 1629990.2435788367580.149990073
#Sta/Elev= 30
       0  896.58    69.9  870.56   121.6  849.19   126.4  846.38   140.8  835.09
   151.1  829.72   169.5  829.15   174.3  828.39   188.7  823.59   203.1  821.71
   368.4  820.72   436.3  817.01  446.75814.3857   448.7  813.99  459.86814.3843
   473.4  818.47   502.3  818.93   523.6  818.14   549.5  821.09   636.9   824.5
   654.4  826.24   667.5  828.68   683.6   834.1   729.9     854   771.6  875.31
   786.7  884.56   798.9  888.03   824.9  903.13   865.6  923.39   879.4  929.42
#Mann= 10 ,-1,0
       0     .05       0      70     .06       0     190     .05       0
  395.18     .06       0  405.18     .05       0  425.18      .1       0
  446.75    .045       0  459.86      .1       0  523.61     .06       0
  603.61      .1       0
Bank Sta=446.75,459.86
XS Rating Curve= 0 ,0
Exp/Cntr(USF)=0,0
Exp/Cntr=0.3,0.1
LCMann Table=0

Chan Stop Cuts=-1
Use User Specified Reach Order=0
Composite Channel Slope=5